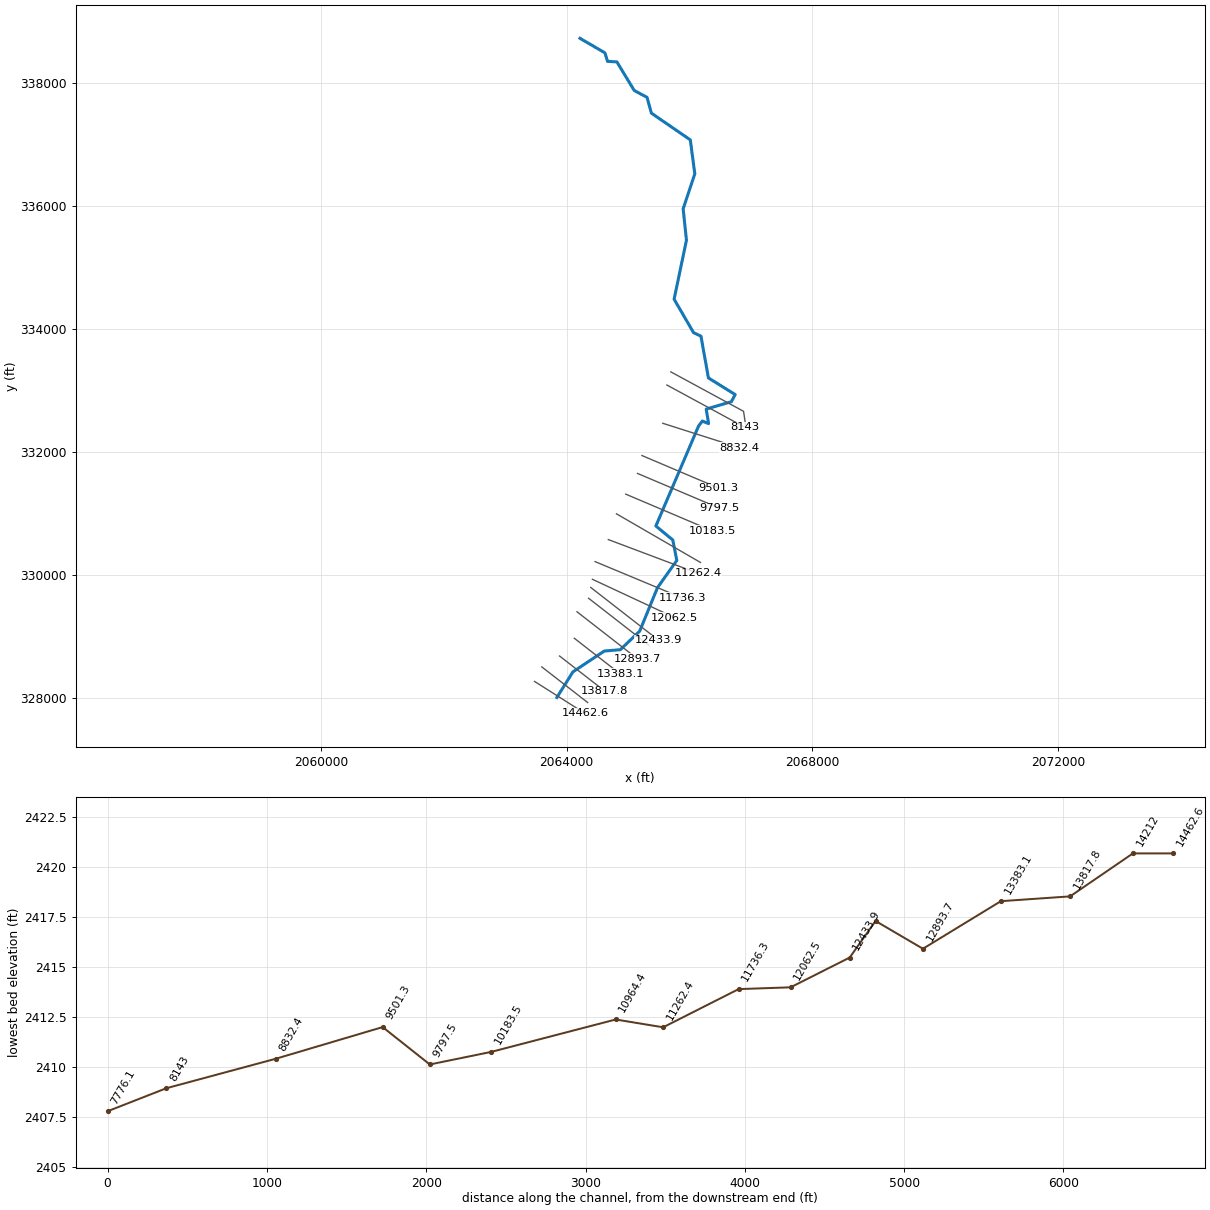
--- MethodstBr.prj (project) ---

Proj Title=MethodstBr
Current Plan=p01
Default Exp/Contr=0,0
English Units
Geom File=g01
Flow File=f01
Plan File=p01
BEGIN DESCRIPTION:
END DESCRIPTION:
DSS Export Rating Curves= 0
DSS Export Rating Curve Sorted= 0
DSS Export Volume Flow Curves= 0
DXF OffsetX= 0
DXF OffsetY= 0
DXF ScaleX= 0
DXF ScaleY= 0

--- MethodstBr.p01 (plan) ---

Plan Title=Floodplain
Program Version=4.00
Geom File=g01
Flow File=f01
K Sum by GR=0
Std Step Tol=0.01
Critical Tol=0.01
Num of Std Step Trials=20
Max Error Tol=0.3
Flow Tol Ratio=0.001
Split Flow NTrial=30
Split Flow Tol=0.02
Split Flow Ratio=0.02
Log Output Level=0
Friction Slope Method=1
Unsteady Friction Slope Method=2
Unsteady Bridges Friction Slope Method=1
Global Log Level=0
CheckData=False
Run HTab=0
Run UNet=0
Run PostProcess=0
UNET Theta=0
UNET Theta Warmup=0
UNET ZTol=0
UNET ZSATol=0
UNET MxIter=0
UNET MaxInSteps=0
UNET DtIC=0
UNET DtMin=0
UNET MaxCRTS=0
UNET WFStab=0
UNET SFStab=0
UNET WFX=0
UNET SFX=0
UNET DSS MLevel=0
UNET DZMax Abort=0
UNET Convert EG Bridges=0
UNET Use Existing IB Tables=0
UNET Froude Limit=0
UNET Froude Power=0
Write IC File=0
Echo Input=False
Echo Output=False
Write Detailed=0

--- MethodstBr.f01 (steady flow) ---

Flow Title=NFF Regression Equation
Program Version=4.00
Number of Profiles=1
Profile Names=P100yr
River Rch & RM=MethodstBr,Main      ,14462.6
519.1744
River Rch & RM=MethodstBr,Main      ,12062.5
554.0152
River Rch & RM=MethodstBr,Main      ,10183.5
614.2113
River Rch & RM=MethodstBr,Main      ,7776.1
649.6235
Boundary for River Rch & Prof#=MethodstBr,Main      ,1
Up Type=0
Dn Type=3
Dn Slope=0.003072

--- MethodstBr.g01 (geometry) ---

Geom Title=USGS 10m DEM
Program Version=4.10

River Reach=MethodstBr      ,Main
Reach XY= 30
     2063841.339      328006.597     2064102.943       328423.79
      2064613.36      328762.332     2064875.512      328784.901
      2065190.73       329087.03     2065480.644      329795.439
     2065794.446      330236.845     2065729.342      330570.178
     2065453.637      330797.054     2066149.818      332425.526
     2066210.775      332505.291     2066312.626      332463.624
     2066273.275      332699.735     2066682.997      332820.106
     2066745.497      332935.847      2066309.54      333206.776
     2066188.205      333885.789     2066066.677      333944.816
     2065750.705      334488.219     2065951.837      335447.429
     2065898.155      335958.311     2066087.842      336529.162
     2066014.473      337080.328     2065380.989      337515.177
     2065309.409      337772.865     2065101.827      337883.814
     2064819.086      338348.752     2064666.084      338357.924
     2064624.478      338496.163     2064218.164      338732.677

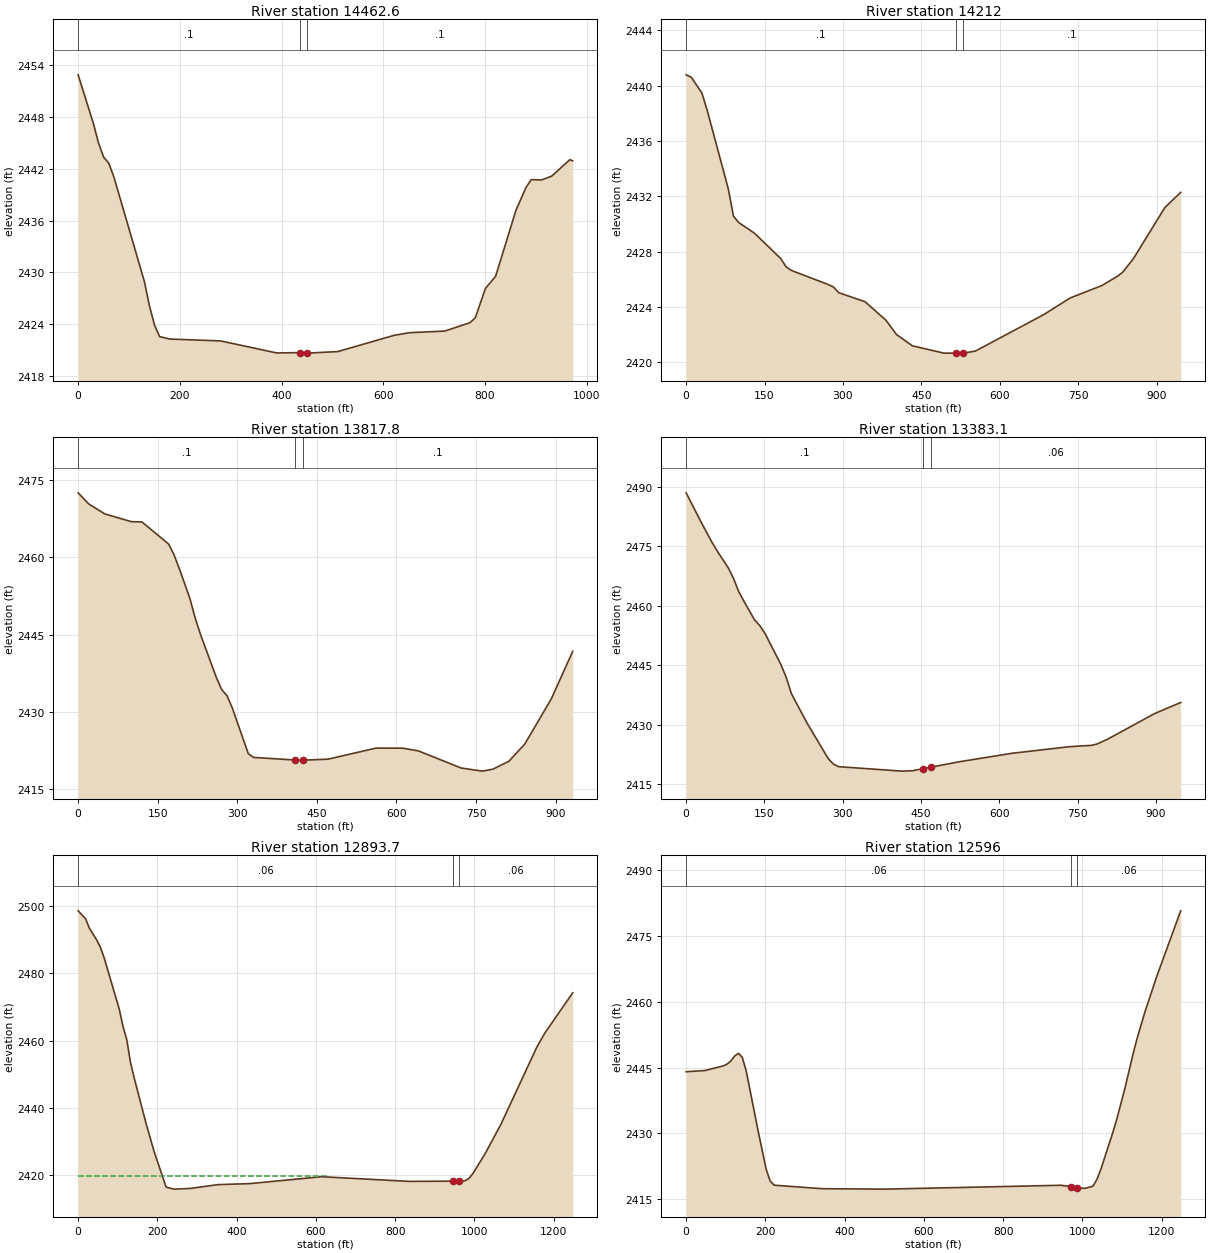
Type RM Length L Ch R = 1 ,14462.6 ,253.9,250.7,246.9
XS GIS Cut Line= 3
     2063477.542      328268.637     2064289.666      327754.552
     2064299.255      327748.481
#Sta/Elev= 30
       0 2452.86      30 2447.23      40 2444.98    50.1 2443.34    60.1 2442.65
    70.1 2441.08   130.2 2428.97   140.2 2426.15   150.2 2423.91   160.2 2422.58
   180.2  2422.3   280.3 2422.08   390.5 2420.69   435.4 2420.73   450.4 2420.67
   510.6 2420.85   620.8 2422.72   650.8 2423.03   720.9 2423.22   770.9  2424.2
   780.9 2424.76     801 2428.16     821 2429.57     861 2437.21   881.1 2439.88
   891.1 2440.74   911.1  2440.7   931.1 2441.14   966.8 2443.04   972.5 2442.92
#Mann= 3 , 0 , 0
       0      .1       0   435.4    .045       0   450.4      .1       0
Bank Sta=435.4,450.4
XS Rating Curve= 0 ,0
Exp/Cntr=0.3,0.1

Type RM Length L Ch R = 1 ,14212   ,395.2,394.1,391.1
XS GIS Cut Line= 2
     2063596.115      328504.564     2064343.608      327924.991
#Sta/Elev= 30
       0 2440.79    10.1 2440.61    30.2 2439.47    40.2 2438.24    80.5 2432.57
    90.6 2430.57   100.6 2430.11   130.8 2429.34   181.1  2427.5   191.2 2426.91
   201.2 2426.65   271.7 2425.63   281.8 2425.45   291.8 2425.04   342.1 2424.39
   382.4 2423.04   402.5 2422.01   432.7  2421.2     493 2420.67   515.5 2420.67
   530.5 2420.67   553.4 2420.82   684.2 2423.46   734.6 2424.66   794.9 2425.55
   825.1 2426.23   835.2 2426.53   855.3 2427.49   915.7  2431.2   945.9 2432.29
#Mann= 3 , 0 , 0
       0      .1       0   515.5    .045       0   530.5      .1       0
Bank Sta=515.5,530.5
XS Rating Curve= 0 ,0
Exp/Cntr=0.3,0.1

Type RM Length L Ch R = 1 ,13817.8 ,432.7,434.7,436.4
XS GIS Cut Line= 2
     2063885.394       328681.76     2064621.978      328110.644
#Sta/Elev= 30
       0 2472.48      20 2470.32    50.1  2468.4   100.2 2466.89   120.3 2466.83
   170.4 2462.56   180.4 2460.55   190.4 2457.86   210.5 2452.05   220.5 2448.21
   230.5 2445.06   260.6 2436.64   270.6 2434.32   280.6 2433.14   290.6 2430.75
   320.7  2421.9   330.7 2421.18     408 2420.68     423 2420.64     471 2420.84
   561.2 2422.98   611.4 2422.97   641.4 2422.44   721.6 2419.13   761.7 2418.52
   781.7  2418.9   811.8 2420.43   841.9 2423.79     892 2432.57   932.1 2441.75
#Mann= 3 , 0 , 0
       0      .1       0     408    .045       0     423      .1       0
#XS Ineff= 2 , 0
                          581.05         2422.97
Permanent Ineff=
       F       F
Bank Sta=408,423
XS Rating Curve= 0 ,0
Exp/Cntr=0.3,0.1

Type RM Length L Ch R = 1 ,13383.1 ,490.8,489.3,485.5
XS GIS Cut Line= 2
     2064125.494      328970.442     2064874.286      328389.862
#Sta/Elev= 30
       0 2488.43    30.2 2480.67    50.4 2475.76    60.5 2473.56    80.6 2469.55
    90.7 2466.89   100.8 2463.51   110.9 2461.07     131 2456.42   141.1 2454.97
   151.2 2452.97   181.4  2445.2   191.5 2442.02   201.6 2437.83   231.8 2430.37
   272.2 2421.44   282.2 2420.05   292.3  2419.4   413.3 2418.28   433.4 2418.37
   453.9 2418.89   468.9 2419.27   524.2 2420.66     625 2422.79   735.8 2424.46
   776.2 2424.77   786.2 2425.07   806.4 2426.25   897.1 2432.76   947.5 2435.58
#Mann= 3 , 0 , 0
       0      .1       0   453.9    .045       0   468.9     .06       0
Bank Sta=453.9,468.9
XS Rating Curve= 0 ,0
Exp/Cntr=0.3,0.1

Type RM Length L Ch R = 1 ,12893.7 ,298.1,297.5,296.9
XS GIS Cut Line= 3
     2064169.376       329401.73     2064281.185      329314.755
     2065154.587       328635.35
#Sta/Elev= 30
       0 2498.63    18.9 2496.27    28.3 2493.48    47.2 2489.89    56.7 2487.65
    66.1 2484.49   103.9 2469.34   113.3 2464.22   122.8 2460.28   132.2 2453.48
   141.6  2448.9   171.8 2435.25     192 2426.97   222.1 2416.49   242.2  2415.9
   282.5  2416.1   352.9 2417.24   433.4 2417.54   614.4 2419.59   835.8  2418.2
   945.7 2418.27   960.7 2418.28   976.6  2418.4   986.6  2419.1   996.7 2420.61
  1026.9 2426.38  1067.1 2435.19  1157.6  2458.1  1177.8 2462.28  1248.2 2474.26
#Mann= 3 , 0 , 0
       0     .06       0   945.7    .045       0   960.7     .06       0
#XS Ineff= 2 , 0
          627.46 2419.67
Permanent Ineff=
       F       F
Bank Sta=945.7,960.7
XS Rating Curve= 0 ,0
Exp/Cntr=0.3,0.1

Type RM Length L Ch R = 1 ,12596   ,161.9,162.1,162.3
XS GIS Cut Line= 3
     2064357.696      329621.991     2064469.505      329535.017
     2065342.906      328855.612
#Sta/Elev= 30
       0 2444.06    47.2 2444.33    94.4  2445.4   103.9 2445.83   113.3 2446.55
   122.8 2447.67   132.2 2448.25   141.6 2447.35   151.7 2444.22   181.9 2430.47
     202 2421.82   212.1 2419.14   222.1 2418.19   342.8 2417.39   503.8 2417.29
   946.4 2418.17   970.7 2417.88   985.7 2417.56  1006.8 2417.47  1026.9 2417.96
  1036.9 2419.53    1047 2421.88  1077.2 2430.28  1087.2 2433.32  1107.4 2440.26
  1127.5 2447.92  1137.5 2451.43  1157.6  2457.6  1187.8  2465.8  1248.2 2480.75
#Mann= 3 , 0 , 0
       0     .06       0   970.7    .045       0   985.7     .06       0
Bank Sta=970.7,985.7
XS Rating Curve= 0 ,0
Exp/Cntr=0.3,0.1

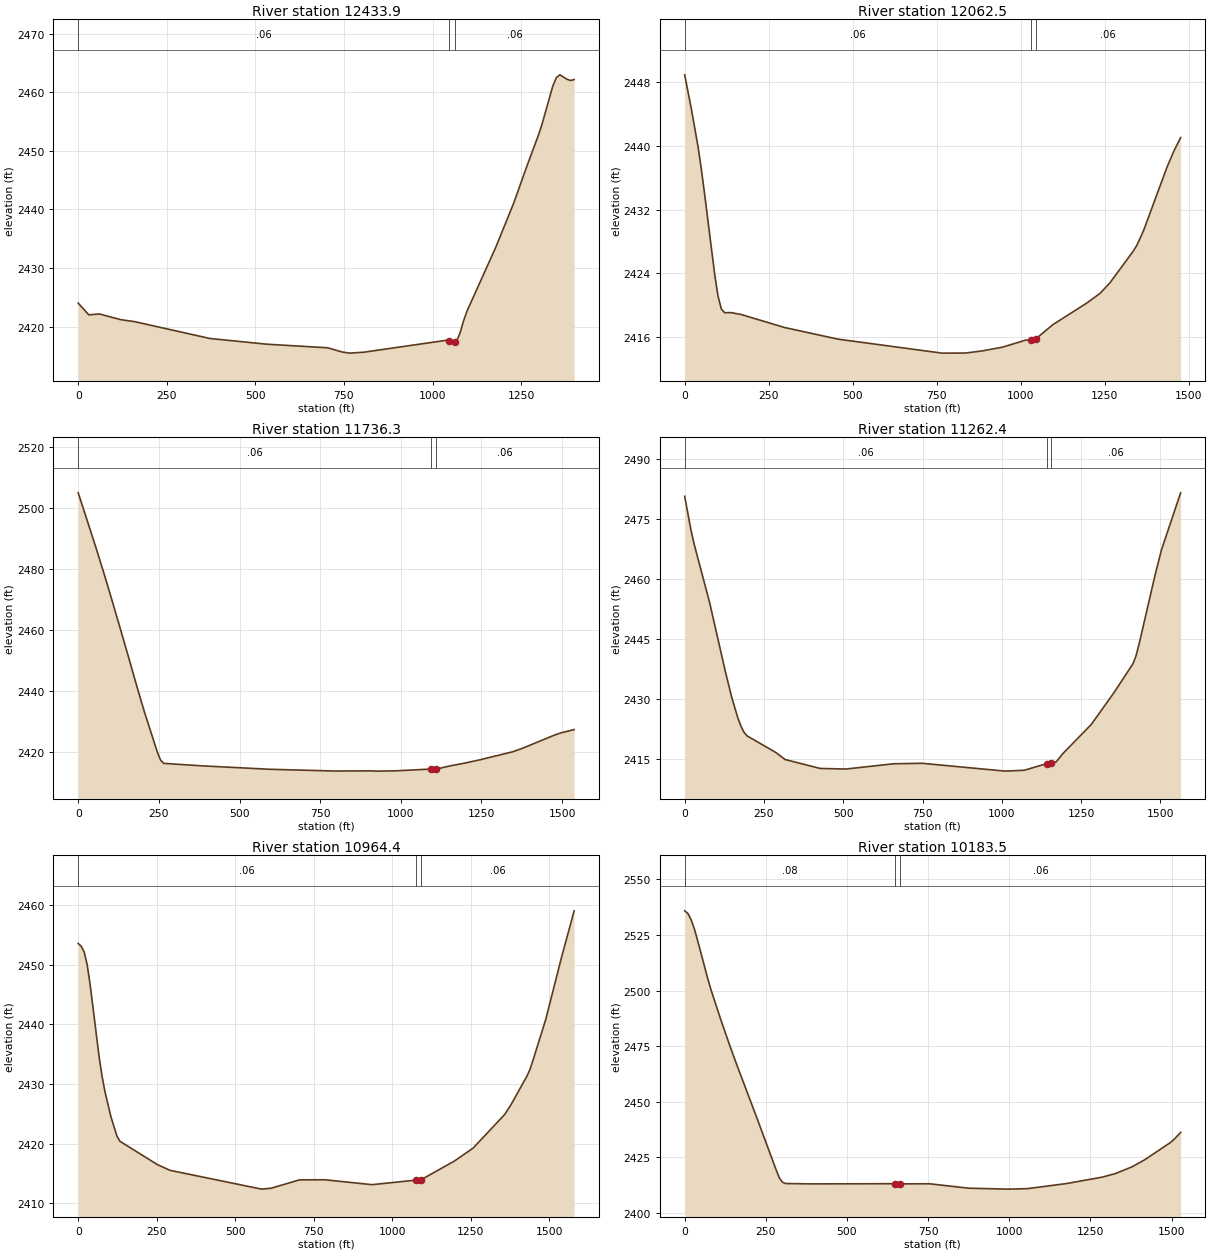
Type RM Length L Ch R = 1 ,12433.9 ,365.9,371.2,376.5
XS GIS Cut Line= 3
     2064393.056      329797.602     2064566.901      329662.371
     2065497.885      328938.173
#Sta/Elev= 30
       0 2423.99      30 2421.99    60.1 2422.14   120.1 2421.17   160.2 2420.82
   371.5 2417.96   532.8 2416.98   704.1 2416.37   744.5 2415.66   764.6 2415.46
     805 2415.61  1036.8 2417.63  1047.1 2417.53    1057 2417.28  1062.1 2417.36
  1067.1 2417.43  1077.1  2418.8  1087.2  2420.9  1097.3 2422.63    1178 2433.45
  1228.4 2440.95  1268.7 2447.76  1298.9 2452.66    1309 2454.51  1339.2 2460.98
  1349.3 2462.46  1359.4 2462.95  1379.6 2462.19  1389.7 2461.98  1399.7 2462.14
#Mann= 3 , 0 , 0
       0     .06       0  1047.1    .045       0  1062.1     .06       0
#XS Ineff= 2 , 0
         1036.67 2417.54
Permanent Ineff=
       F       F
Bank Sta=1047.1,1062.1
XS Rating Curve= 0 ,0
Exp/Cntr=0.3,0.1

Type RM Length L Ch R = 1 ,12062.5 ,325.6,326.1,326.7
XS GIS Cut Line= 3
     2064420.641      329930.035     2064851.788      329729.242
     2065758.533      329306.956
#Sta/Elev= 30
       0 2448.95    19.8 2444.69    39.6 2439.96    49.5 2437.13    59.4 2433.94
    89.2 2423.91    99.1 2421.17     109 2419.53   118.9 2419.05   138.7 2419.06
   168.4 2418.82   297.3 2417.19   455.8 2415.73   765.7 2413.97   835.7 2413.98
   885.7 2414.25   945.7 2414.72  1015.8 2415.62  1029.5 2415.65  1044.5 2415.75
  1095.8 2417.55  1195.8 2420.24  1235.8 2421.47  1265.8 2422.82  1335.8 2426.84
  1345.8 2427.53  1365.8 2429.39  1435.9  2437.4  1455.9 2439.37  1475.9 2441.06
#Mann= 3 , 0 , 0
       0     .06       0  1029.5    .045       0  1044.5     .06       0
Bank Sta=1029.5,1044.5
XS Rating Curve= 0 ,0
Exp/Cntr=0.3,0.1

Type RM Length L Ch R = 1 ,11736.3 ,474.1,473.9,473.2
XS GIS Cut Line= 3
     2064463.739      330217.886     2064771.832      330089.569
     2065882.798      329626.867
#Sta/Elev= 30
       0 2505.08    39.3 2492.28    58.9 2485.79    78.5 2479.13    98.2 2472.18
   127.6 2461.62   157.1 2450.83   176.7 2443.52   196.3 2436.43   206.1 2432.98
   245.4 2420.09   255.2 2417.51     265 2416.42   383.9 2415.61   594.5 2414.48
   795.1 2413.91   905.4 2413.97   925.4 2413.88   985.6 2413.98  1093.6 2414.56
  1108.6 2414.62    1116 2414.69  1146.1 2415.45  1196.2 2416.47  1246.4 2417.62
  1346.7 2420.22  1376.8 2421.36    1477 2425.72  1497.1 2426.44  1537.2  2427.5
#Mann= 3 , 0 , 0
       0     .06       0  1093.6    .045       0  1108.6     .06       0
Bank Sta=1093.6,1108.6
XS Rating Curve= 0 ,0
Exp/Cntr=0.3,0.1

Type RM Length L Ch R = 1 ,11262.4 ,304.6,297.9,291.1
XS GIS Cut Line= 3
     2064679.824      330576.492     2064910.414      330489.697
     2066143.451      330025.579
#Sta/Elev= 30
       0 2480.74    19.7 2472.37    29.6 2468.86    78.8  2454.1   128.1 2436.95
   147.8 2430.61   167.5 2425.32   177.4 2423.24   187.2 2421.69   197.1 2420.77
   286.6 2416.68   316.8 2414.87   427.4 2412.64   507.9 2412.49   658.7 2413.81
   749.2 2413.93  1010.7 2411.97  1071.1 2412.19  1141.5 2413.85  1156.5 2413.88
  1171.6 2414.28  1191.8 2416.29  1282.3 2423.66  1352.7 2431.49    1413 2438.75
  1423.1 2440.77  1433.1 2443.81  1483.4 2461.05  1503.5 2467.32  1563.9 2481.61
#Mann= 3 , 0 , 0
       0     .06       0  1141.5    .045       0  1156.5     .06       0
Bank Sta=1141.5,1156.5
XS Rating Curve= 0 ,0
Exp/Cntr=0.3,0.1

Type RM Length L Ch R = 1 ,10964.4 ,780.6,780.8,758.9
XS GIS Cut Line= 3
     2064812.168      330995.501     2064943.462      330919.564
     2066179.591      330204.621
#Sta/Elev= 30
       0 2453.54     9.5 2453.08      19 2452.11    28.4 2450.02    37.9 2446.68
    66.4 2434.63    75.8 2431.33    85.3 2428.68   104.3 2424.46   123.2 2421.28
   132.7 2420.39   252.2 2416.47   292.5 2415.51   584.1 2412.36   614.3 2412.51
   704.8 2413.91   785.2 2413.93   936.1 2413.11    1076 2413.87    1091  2413.9
  1197.5 2417.04  1257.9 2419.24  1358.4 2424.87  1378.5 2426.51  1428.8 2431.25
  1438.9  2432.4  1448.9 2434.01  1489.2  2440.8  1539.4  2451.2  1579.7 2459.01
#Mann= 3 , 0 , 0
       0     .06       0    1076    .045       0    1091     .06       0
Bank Sta=1076,1091
XS Rating Curve= 0 ,0
Exp/Cntr=0.3,0.1

Type RM Length L Ch R = 1 ,10183.5 ,386,386,386
XS GIS Cut Line= 2
     2064963.056      331315.877      2066369.69      330719.123
#Sta/Elev= 30
       0 2535.89      10 2534.69    20.1 2531.81    30.2 2527.59    40.2 2522.37
    70.4 2505.77    80.4  2500.7   110.6 2487.24   140.7 2474.58   160.8 2466.58
   221.2 2443.26   281.5 2419.54   291.5 2415.85   301.6 2413.79   311.6 2413.25
     392  2413.1   649.4 2413.18   664.4 2413.09   753.9 2413.16   874.6 2411.16
   995.2 2410.74  1055.5 2410.95  1176.2 2413.24  1286.7 2416.14  1326.9 2417.73
  1377.2 2420.69  1417.4 2423.94  1497.8 2431.81  1507.9 2433.14    1528 2436.25
#Mann= 3 , 0 , 0
       0     .08       0   649.4    .045       0   664.4     .06       0
Bank Sta=649.4,664.4
XS Rating Curve= 0 ,0
Exp/Cntr=0.3,0.1

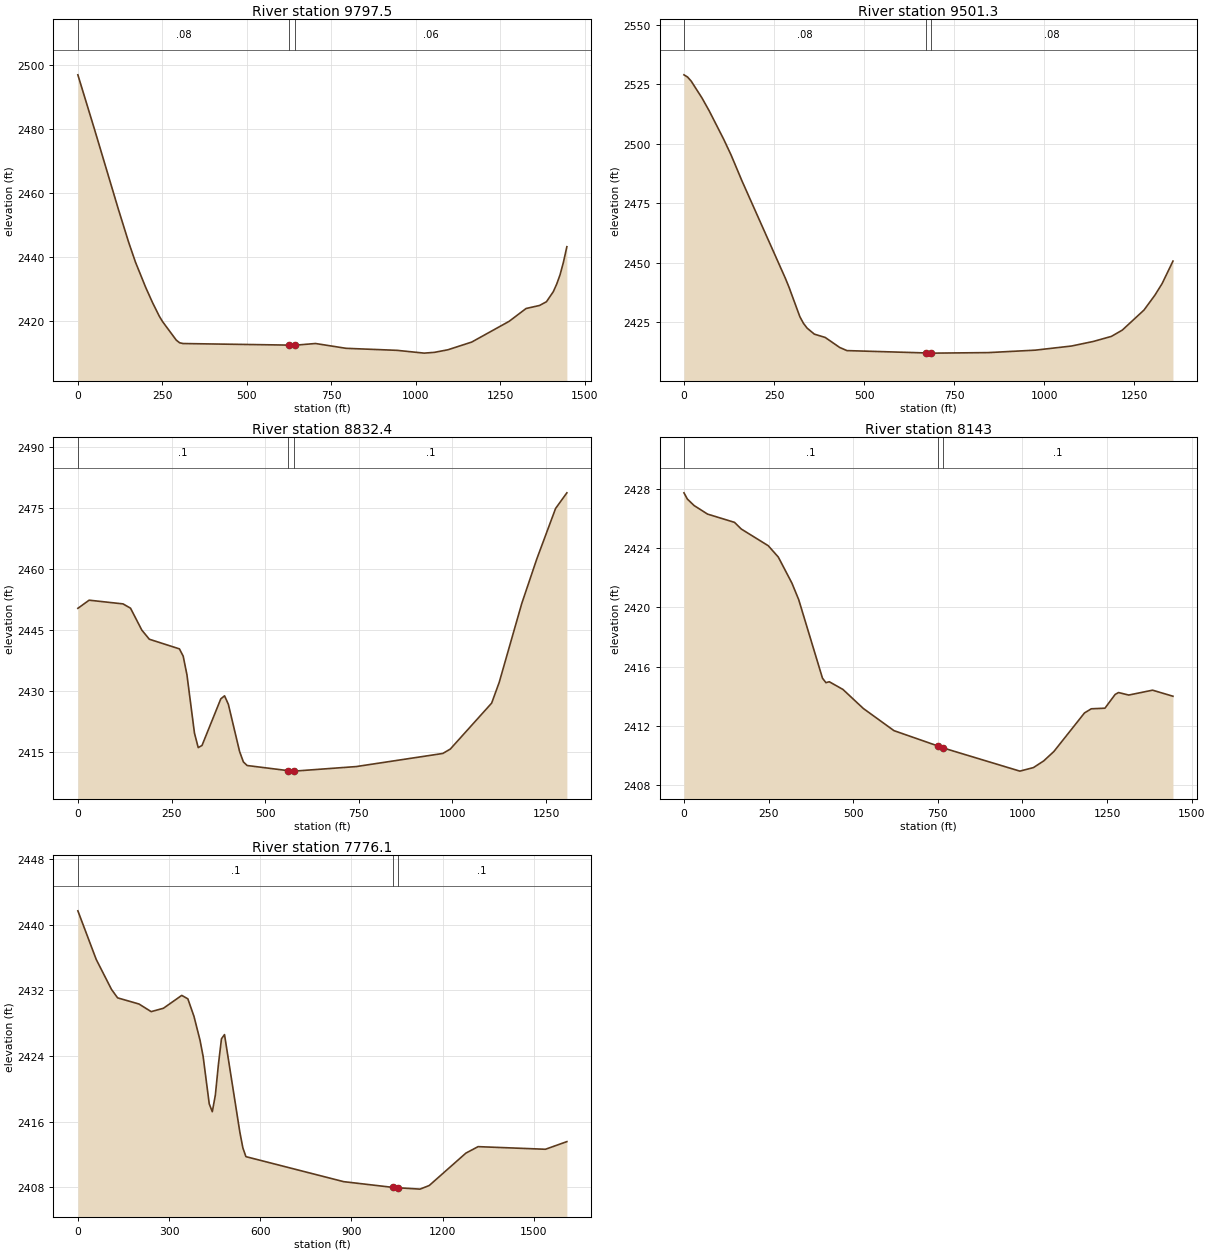
Type RM Length L Ch R = 1 ,9797.5  ,296.2,296.2,296.2
XS GIS Cut Line= 3
     2065154.559      331653.031     2065172.612      331645.373
     2066486.515      331087.959
#Sta/Elev= 30
       0 2496.87    49.8 2479.68   120.1 2454.88   150.3 2444.67   170.4 2438.49
   200.5 2430.65   220.6 2425.94   240.7 2421.66   250.8 2419.91     291 2414.19
     301 2413.34   311.1  2413.1     626 2412.61     641 2412.56   703.1 2413.11
   793.5 2411.61   944.3 2410.98  1024.7 2410.11  1054.9 2410.35  1095.1 2411.16
  1165.4 2413.56    1276 2420.02  1326.2 2424.02  1366.4 2424.98  1386.6 2426.14
  1406.7 2429.26  1416.7  2431.6  1426.8 2434.56  1436.8 2438.48  1446.9 2443.28
#Mann= 3 , 0 , 0
       0     .08       0     626    .045       0     641     .06       0
Bank Sta=626,641
XS Rating Curve= 0 ,0
Exp/Cntr=0.3,0.1

Type RM Length L Ch R = 1 ,9501.3  ,666.8,668.9,671
XS GIS Cut Line= 2
     2065226.883      331944.128     2066476.038      331414.183
#Sta/Elev= 30
       0 2528.92      10 2527.99    20.1 2526.27    50.3 2519.12    70.4 2513.68
   110.6 2501.74   130.7 2495.25   160.8 2484.41   281.4 2443.42   291.5 2439.68
   321.6 2427.28   331.7 2424.48   341.7 2422.49   361.8 2419.96     392 2418.56
   432.2 2414.35   452.3 2413.04     671 2412.06     686    2412   693.5 2411.98
   844.3  2412.2     975 2413.23  1075.5 2414.97  1135.8 2416.88    1186 2419.01
  1216.2 2421.64  1276.5 2430.08  1306.7 2436.32  1326.8  2441.2  1356.9 2450.65
#Mann= 3 , 0 , 0
       0     .08       0     671    .045       0     686     .08       0
Bank Sta=671,686
XS Rating Curve= 0 ,0
Exp/Cntr=0.3,0.1

Type RM Length L Ch R = 1 ,8832.4  ,687.5,689.2,682.9
XS GIS Cut Line= 2
     2065566.043       332468.78     2066810.046      332072.988
#Sta/Elev= 30
       0 2450.42    30.1 2452.42   120.5 2451.51   140.6 2450.45   170.7 2445.07
   190.8 2442.82   271.1 2440.45   281.2 2438.66   291.2 2434.08   311.3 2419.74
   321.3 2416.18   331.4 2416.71   381.6 2428.17   391.6 2428.91   401.7 2426.84
   431.8  2415.2   441.8 2412.67   451.9 2411.78   562.2 2410.51   572.4  2410.4
   577.2  2410.4   743.1 2411.52   974.1 2414.74   994.2 2415.82  1104.6 2427.12
  1124.7  2432.2    1185 2451.61  1225.1 2462.55  1275.3 2474.97  1305.4 2478.81
#Mann= 3 , 0 , 0
       0      .1       0   562.2    .045       0   577.2      .1       0
Bank Sta=562.2,577.2
XS Rating Curve= 0 ,0
Exp/Cntr=0.3,0.1

Type RM Length L Ch R = 1 ,8143    ,357.5,368.4,370.9
XS GIS Cut Line= 3
     2065632.861      333091.655     2065895.512      332949.293
     2066903.097      332403.165
#Sta/Elev= 30
       0 2427.76      10 2427.34    29.9  2426.9    69.7 2426.32   149.4 2425.76
   169.3 2425.31     249 2424.18   278.8 2423.41   318.9 2421.65     339 2420.53
   409.3 2415.21   419.4 2414.91   429.4 2414.97   469.7 2414.45     530 2413.16
   620.5 2411.66   750.6 2410.62   765.6 2410.49   992.4 2408.92  1032.6 2409.16
  1062.8 2409.61    1093 2410.25  1183.4 2412.86  1203.6 2413.14  1243.8 2413.18
  1273.9 2414.11    1284 2414.24  1314.1 2414.07  1384.5  2414.4  1444.8 2413.99
#Mann= 3 , 0 , 0
       0      .1       0   750.6    .045       0   765.6      .1       0
Bank Sta=750.6,765.6
XS Rating Curve= 0 ,0
Exp/Cntr=0.3,0.1

Type RM Length L Ch R = 1 ,7776.1  ,7709.3,7774,7833.7
XS GIS Cut Line= 3
     2065697.607      333305.318     2066881.627       332663.56
      2066920.48      332404.582
#Sta/Elev= 30
       0  2441.7    60.3 2435.78   110.6 2432.12   130.7 2431.09     201 2430.34
   241.2 2429.41   281.4 2429.82   341.7 2431.39   361.8 2430.97   381.9 2428.84
     402  2425.9   412.1 2423.94   432.2 2418.16   442.2 2417.21   452.3 2419.24
   462.3 2422.95   472.4  2426.1   482.4 2426.61   532.7 2414.75   542.7 2412.81
   552.8 2411.73   874.4 2408.68  1036.5 2407.98  1051.5 2407.94  1125.6 2407.77
  1155.8 2408.21  1276.4 2412.16  1316.6 2412.95  1538.1 2412.63  1608.6 2413.56
#Mann= 3 , 0 , 0
       0      .1       0  1036.5    .045       0  1051.5      .1       0
Bank Sta=1036.5,1051.5
XS Rating Curve= 0 ,0
Exp/Cntr=0.3,0.1

Chan Stop Cuts=-1
Use User Specified Reach Order=0
Composite Channel Slope=5